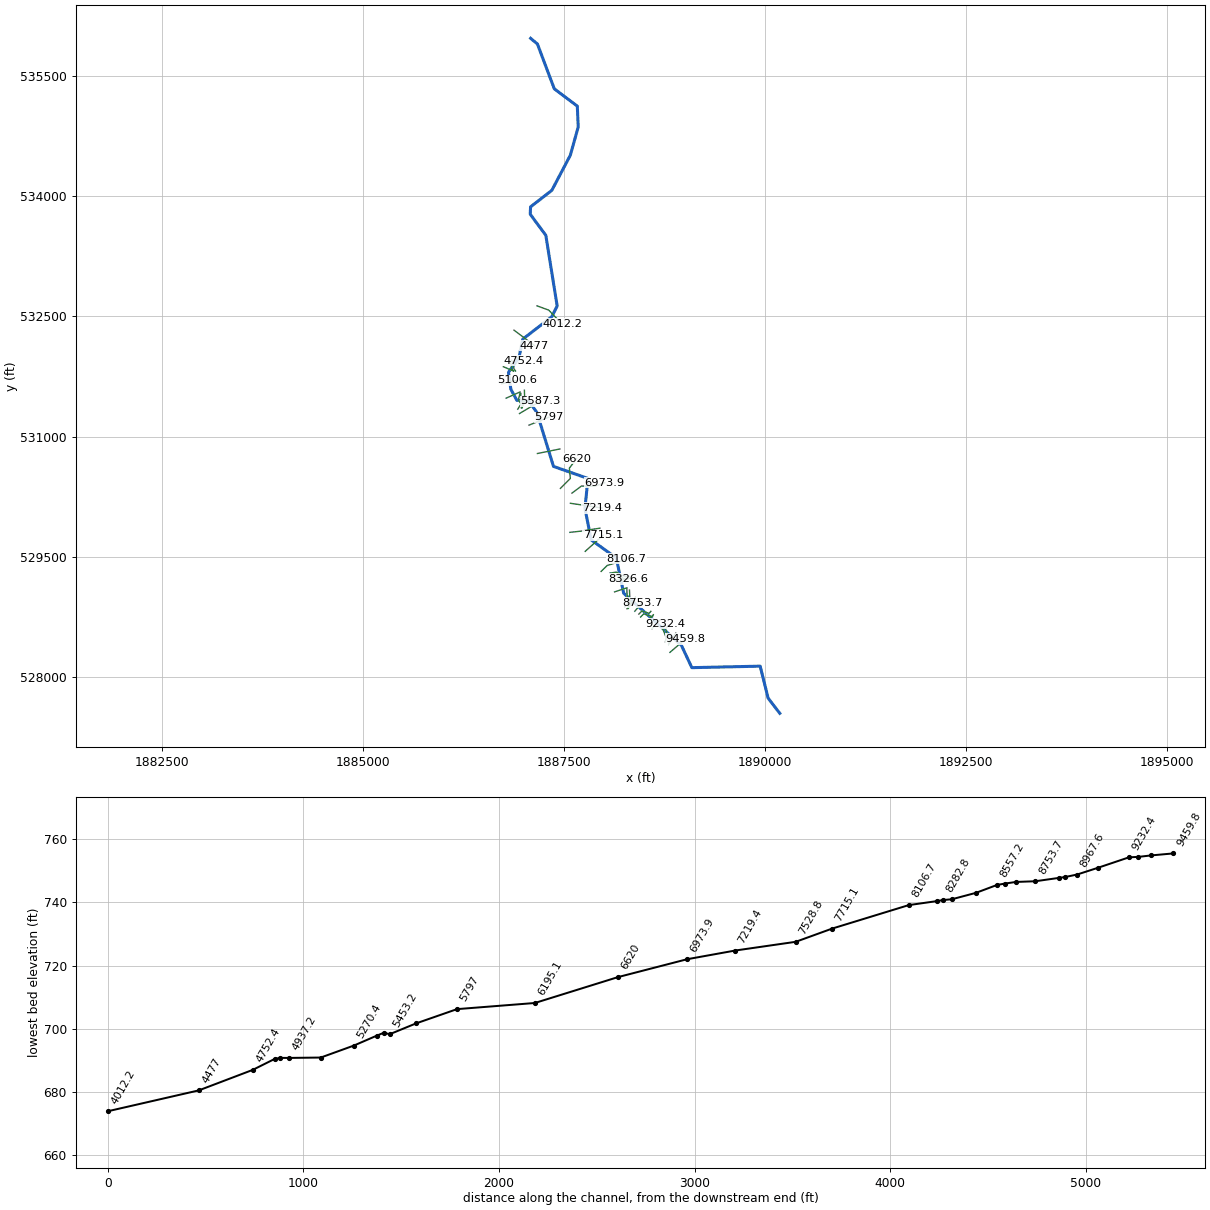
--- QUENSHLSCK.prj (project) ---

Proj Title=QUENSHLSCK
Current Plan=p01
Default Exp/Contr=0,0
English Units
Geom File=g01
Flow File=f01
Plan File=p01
BEGIN DESCRIPTION:
END DESCRIPTION:
DSS Export Rating Curves= 0
DSS Export Rating Curve Sorted= 0
DSS Export Volume Flow Curves= 0
DXF OffsetX= 0
DXF OffsetY= 0
DXF ScaleX= 0
DXF ScaleY= 0

--- QUENSHLSCK.p01 (plan) ---

Plan Title=Floodplain
Program Version=4.00
Geom File=g01
Flow File=f01
K Sum by GR=0
Std Step Tol=0.01
Critical Tol=0.01
Num of Std Step Trials=20
Max Error Tol=0.3
Flow Tol Ratio=0.001
Split Flow NTrial=30
Split Flow Tol=0.02
Split Flow Ratio=0.02
Log Output Level=0
Friction Slope Method=1
Unsteady Friction Slope Method=2
Unsteady Bridges Friction Slope Method=1
Global Log Level=0
CheckData=False
Run HTab=0
Run UNet=0
Run PostProcess=0
UNET Theta=0
UNET Theta Warmup=0
UNET ZTol=0
UNET ZSATol=0
UNET MxIter=0
UNET MaxInSteps=0
UNET DtIC=0
UNET DtMin=0
UNET MaxCRTS=0
UNET WFStab=0
UNET SFStab=0
UNET WFX=0
UNET SFX=0
UNET DSS MLevel=0
UNET DZMax Abort=0
UNET Convert EG Bridges=0
UNET Use Existing IB Tables=0
UNET Froude Limit=0
UNET Froude Power=0
Write IC File=0
Echo Input=False
Echo Output=False
Write Detailed=0

--- QUENSHLSCK.f01 (steady flow) ---

Flow Title=NFF Regression Equation
Program Version=4.10
Number of Profiles= 1
Profile Names=P100yr
River Rch & RM=QUENSHLSCK,Main            ,9459.8
1209.807
River Rch & RM=QUENSHLSCK,Main            ,5587.3
1305.878
River Rch & RM=QUENSHLSCK,Main            ,1649
1443.181
River Rch & RM=QUENSHLSCK,Main            ,1288.3
1746.281
River Rch & RM=QUENSHLSCK,Main            ,537.3
1751.306
Boundary for River Rch & Prof#=QUENSHLSCK,Main            , 1
Up Type= 0
Dn Type= 3
Dn Slope=0.016
DSS Import GetInterval= 0
DSS Import GetPeak= 0
DSS Import FillOption= 0

--- QUENSHLSCK.g01 (geometry) ---

Geom Title=USGS 10m DEM
Program Version=4.10

River Reach=QUENSHLSCK      ,Main
Reach XY= 30
     1890187.013      527548.674      1890041.44      527738.518
     1889942.482      528137.476     1889092.341      528118.804
     1888962.186      528397.155      1888243.87      529046.894
      1888152.16      529486.673     1887840.099      529711.741
     1887761.735      530104.597     1887800.105      530478.074
      1887370.78      530628.296     1887165.258      531297.624
     1887064.677      531443.866     1886914.689      531451.869
     1886839.595       531591.86     1886810.192      531801.798
     1886940.559      531981.339     1886987.824      532215.193
     1887348.936       532494.62     1887416.161      532629.227
     1887275.236      533510.149     1887081.104       533773.17
      1887085.28      533865.276     1887349.854      534071.086
     1887579.692      534507.995     1887678.214      534861.702
     1887667.042      535121.086     1887380.536      535337.554
     1887170.466      535896.582      1887086.05      535966.784

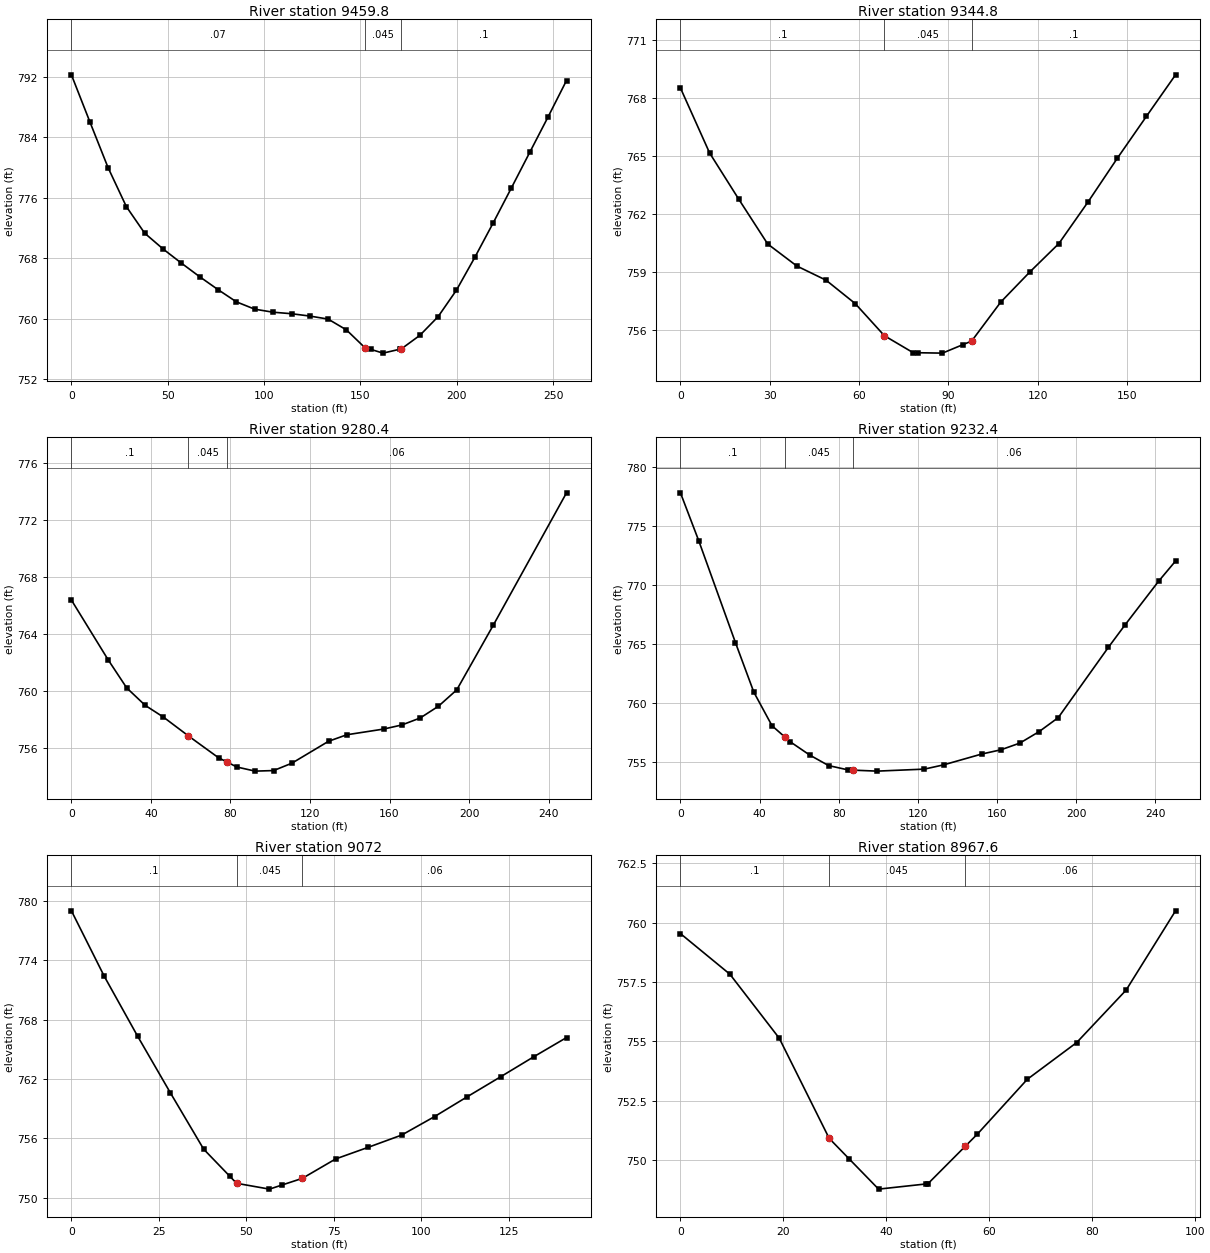
Type RM Length L Ch R = 1 ,9459.8  ,108.4,115.1,121.7
XS GIS Cut Line= 2
     1888819.845      528309.582     1889014.599      528477.052
#Sta/Elev= 30
       0  792.23     9.5  786.06      19  779.97    28.5  774.81      38   771.3
    47.6   769.2    57.1  767.33    66.6  765.53    76.1  763.83    85.6  762.22
    95.1  761.25   104.6  760.85   114.2  760.65   123.7  760.34   133.2  759.94
   142.7  758.51   152.2  756.18   155.3  755.94   161.7  755.44   170.3  755.95
   171.2     756   180.8  757.79   190.3  760.27   199.8  763.77   209.3  768.09
   218.8  772.63   228.3  777.28   237.8  781.97   247.3  786.65   256.9  791.48
#Mann= 3 , 0 , 0
       0     .07       0   152.2    .045       0   171.2      .1       0
Bank Sta=152.2,171.2
XS Rating Curve= 0 ,0
Exp/Cntr=0.3,0.1

Type RM Length L Ch R = 1 ,9344.8  ,34.1,64.3,92.7
XS GIS Cut Line= 2
     1888803.331      528409.254     1888892.351      528549.682
#Sta/Elev= 20
       0   768.5     9.8  765.14    19.6  762.75    29.3  760.44    39.1   759.3
    48.9  758.57    58.7  757.36    68.5   755.7    78.2  754.82    79.9  754.82
      88   754.8    94.9  755.24    97.8  755.42   107.6  757.44   117.4     759
   127.1  760.46   136.9  762.61   146.7  764.86   156.5  767.03   166.3  769.18
#Mann= 3 , 0 , 0
       0      .1       0    68.5    .045       0    97.8      .1       0
Bank Sta=68.5,97.8
XS Rating Curve= 0 ,0
Exp/Cntr=0.3,0.1

Type RM Length L Ch R = 1 ,9280.4  ,49.9,48,49.7
XS GIS Cut Line= 4
     1888805.039       528416.49     1888814.067      528471.351
      1888764.81      528600.484      1888797.48      528644.971
#Sta/Elev= 21
       0  766.38    18.5  762.17    27.8   760.2    37.1  758.97    46.3  758.14
  58.831756.8199      74  755.28  78.418754.9679    83.2  754.63    92.4  754.34
   101.7  754.38   110.9   754.9   129.3  756.44   138.5   756.9     157   757.3
   166.2  757.59   175.4  758.08   184.6  758.91   193.8  760.06   212.2  764.62
     249  773.93
#Mann= 3 , 0 , 0
       0      .1       0  58.831    .045       0  78.418     .06       0
Bank Sta=58.831,78.418
XS Rating Curve= 0 ,0
Skew Angle= 45
Exp/Cntr=0.3,0.1

Type RM Length L Ch R = 1 ,9232.4  ,192.7,160.4,126.2
XS GIS Cut Line= 4
     1888763.693      528439.104     1888772.721      528493.966
      1888724.47      528620.462     1888759.447      528668.376
#Sta/Elev= 23
       0  777.82     9.3  773.73    27.8  765.11    37.1   760.9    46.3  758.05
  52.962757.0686    55.6  756.68    65.3  755.57    74.9  754.67    84.6  754.31
  87.186754.2834    99.4   754.2   123.3  754.37     133  754.73   152.3  755.65
     162  756.01   171.6  756.58   181.3  757.55     191  758.74   216.4  764.72
   224.9  766.64   241.8  770.33   250.3  772.03
#Mann= 3 , 0 , 0
       0      .1       0  52.962    .045       0  87.186     .06       0
Bank Sta=52.962,87.186
XS Rating Curve= 0 ,0
Skew Angle= 45
Exp/Cntr=0.3,0.1

Type RM Length L Ch R = 1 ,9072    ,105.6,104.4,103
XS GIS Cut Line= 2
     1888596.292      528605.125     1888692.126      528709.292
#Sta/Elev= 18
       0  779.01     9.4  772.38    18.9  766.34    28.3  760.59    37.8   754.9
    45.3  752.15    47.2  751.45    56.6  750.86    60.3  751.29      66  751.95
    75.5  753.91    84.9   755.1    94.4  756.33   103.8   758.2   113.2  760.22
   122.7  762.23   132.1  764.24   141.5  766.19
#Mann= 3 , 0 , 0
       0      .1       0    47.2    .045       0      66     .06       0
Bank Sta=47.2,66
XS Rating Curve= 0 ,0
Exp/Cntr=0.3,0.1

Type RM Length L Ch R = 1 ,8967.6  ,88.2,61.1,27.3
XS GIS Cut Line= 2
     1888539.677      528698.834     1888608.932      528765.658
#Sta/Elev= 14
       0  759.54     9.6  757.83    19.2  755.13    28.9  750.91    32.8  750.04
    38.5  748.77    47.8  748.99    48.1     749    55.3750.5675    57.7  751.09
    67.4   753.4      77  754.95    86.6  757.16    96.2   760.5
#Mann= 3 , 0 , 0
       0      .1       0    28.9    .045       0    55.3     .06       0
Bank Sta=28.9,55.3
XS Rating Curve= 0 ,0
Exp/Cntr=0.3,0.1

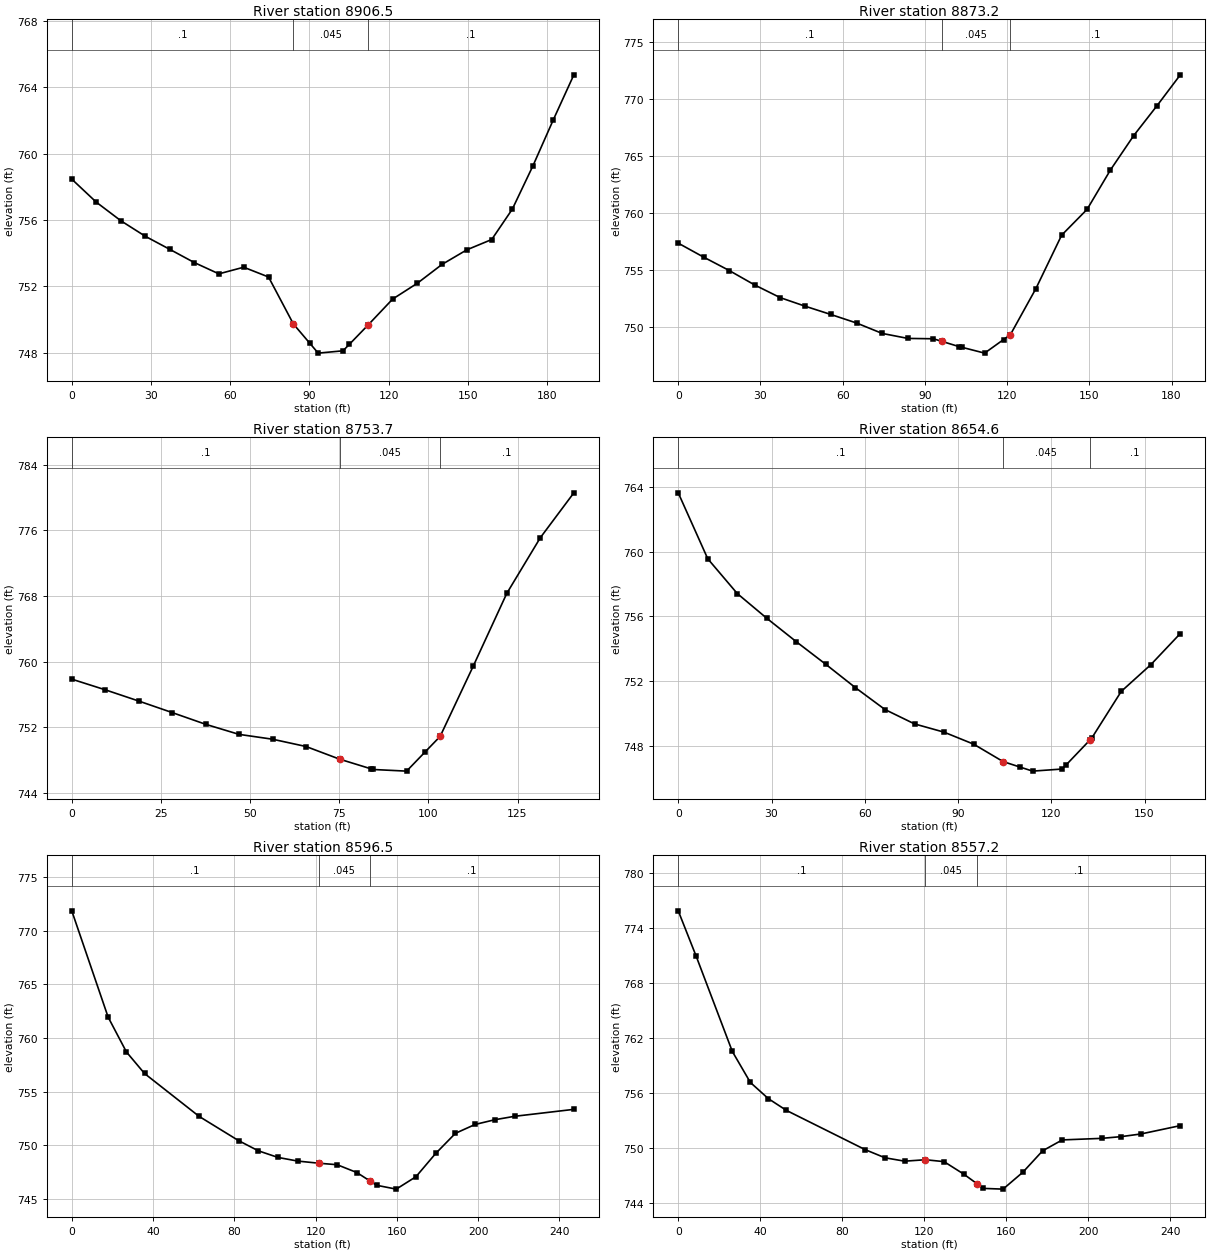
Type RM Length L Ch R = 1 ,8906.5  ,42.5,33.3,40.4
XS GIS Cut Line= 4
     1888454.637      528750.392     1888493.899      528789.944
     1888591.458       528755.97      1888612.92      528778.415
#Sta/Elev= 24
       0  758.47     9.3  757.08    18.6  755.96    27.9  755.02    37.2  754.23
    46.4  753.44    55.7  752.76    65.1  753.16    74.5  752.57    83.9  749.74
    90.1  748.58    93.3  747.98   102.7  748.12   105.1  748.51   112.1  749.66
   121.5  751.24   130.9   752.2   140.2  753.33   149.6  754.21     159  754.83
   166.8  756.66   174.6  759.27   182.3  762.04   190.1  764.76
#Mann= 3 , 0 , 0
       0      .1       0    83.9    .045       0   112.1      .1       0
Bank Sta=83.9,112.1
XS Rating Curve= 0 ,0
Exp/Cntr=0.3,0.1

Type RM Length L Ch R = 1 ,8873.2  ,80.6,119.6,148.6
XS GIS Cut Line= 4
     1888432.832      528786.838     1888472.094       528826.39
     1888560.368       528795.65     1888582.505      528821.504
#Sta/Elev= 24
       0  757.34     9.3  756.11    18.6  754.94    27.9  753.67    37.2  752.56
    46.4   751.8    55.7  751.08    65.1  750.33    74.4  749.42    83.8  748.98
    93.1  748.95    96.2748.7225   102.5  748.26   103.7  748.19   111.8  747.69
   118.7  748.88   121.2  749.31   130.5  753.35   139.9  758.04   149.2  760.31
   157.7  763.76   166.2  766.78   174.7   769.4   183.2  772.11
#Mann= 3 , 0 , 0
       0      .1       0    96.2    .045       0   121.2      .1       0
Bank Sta=96.2,121.2
XS Rating Curve= 0 ,0
Exp/Cntr=0.3,0.1

Type RM Length L Ch R = 1 ,8753.7  ,96.5,99.1,102
XS GIS Cut Line= 2
     1888382.186      528821.974     1888472.464      528930.046
#Sta/Elev= 18
       0  757.85     9.4  756.55    18.8  755.18    28.2  753.77    37.6  752.34
    46.9  751.12    56.3  750.53    65.7  749.64    75.1   748.1      84  746.91
    84.5  746.84    93.9  746.64      99  748.94   103.3  750.87   112.6  759.45
     122  768.31   131.4  775.09   140.8  780.56
#Mann= 3 , 0 , 0
       0      .1       0    75.1    .045       0   103.3      .1       0
Bank Sta=75.1,103.3
XS Rating Curve= 0 ,0
Exp/Cntr=0.3,0.1

Type RM Length L Ch R = 1 ,8654.6  ,41.5,58,74.2
XS GIS Cut Line= 2
     1888301.019      528857.549      1888389.04      528992.966
#Sta/Elev= 21
       0  763.63     9.5  759.55      19   757.4    28.5  755.87      38  754.42
    47.5  753.02      57  751.58    66.5  750.23      76  749.34    85.5  748.83
      95  748.09   104.5  747.01   109.8  746.68     114  746.42   123.5  746.55
   124.8  746.81   132.3748.3192     133  748.46   142.5  751.35     152     753
   161.5  754.93
#Mann= 3 , 0 , 0
       0      .1       0   104.5    .045       0   132.3      .1       0
Bank Sta=104.5,132.3
XS Rating Curve= 0 ,0
Exp/Cntr=0.3,0.1

Type RM Length L Ch R = 1 ,8596.5  ,40.2,39.3,40.1
XS GIS Cut Line= 3
     1888285.394      528852.861      1888324.45      528901.867
     1888316.121      529086.073
#Sta/Elev= 22
       0  771.88    17.9  761.95    26.9   758.7    35.8  756.69    62.7  752.68
    82.1  750.42    91.8  749.47   101.5  748.85   111.2  748.51 121.503748.3107
   130.6  748.17   140.3  747.44 146.705746.6575     150  746.25   159.7  745.89
   169.4  747.05   179.1  749.22   188.8   751.1   198.5  751.93   208.2  752.37
   217.9  752.69   247.1  753.34
#Mann= 3 , 0 , 0
       0      .1       0 121.503    .045       0 146.705      .1       0
Bank Sta=121.503,146.705
XS Rating Curve= 0 ,0
Skew Angle= 30
Exp/Cntr=0.3,0.1

Type RM Length L Ch R = 1 ,8557.2  ,137.3,106.8,74.2
XS GIS Cut Line= 3
     1888257.269      528874.216     1888291.612      528914.365
     1888282.931      529106.357
#Sta/Elev= 22
       0  775.83     8.8  770.85    26.4  760.48    35.2   757.1      44  755.33
    52.8  754.05    91.3  749.76   100.9  748.88   110.5  748.51 120.637748.6677
   129.7  748.46   139.3   747.1 145.665746.0687   148.9  745.54   158.5  745.46
   168.2  747.31   177.8  749.64   187.4  750.83   206.6     751   216.2  751.19
   225.8  751.48     245  752.39
#Mann= 3 , 0 , 0
       0      .1       0 120.637    .045       0 145.665      .1       0
Bank Sta=120.637,145.665
XS Rating Curve= 0 ,0
Skew Angle= 30
Exp/Cntr=0.3,0.1

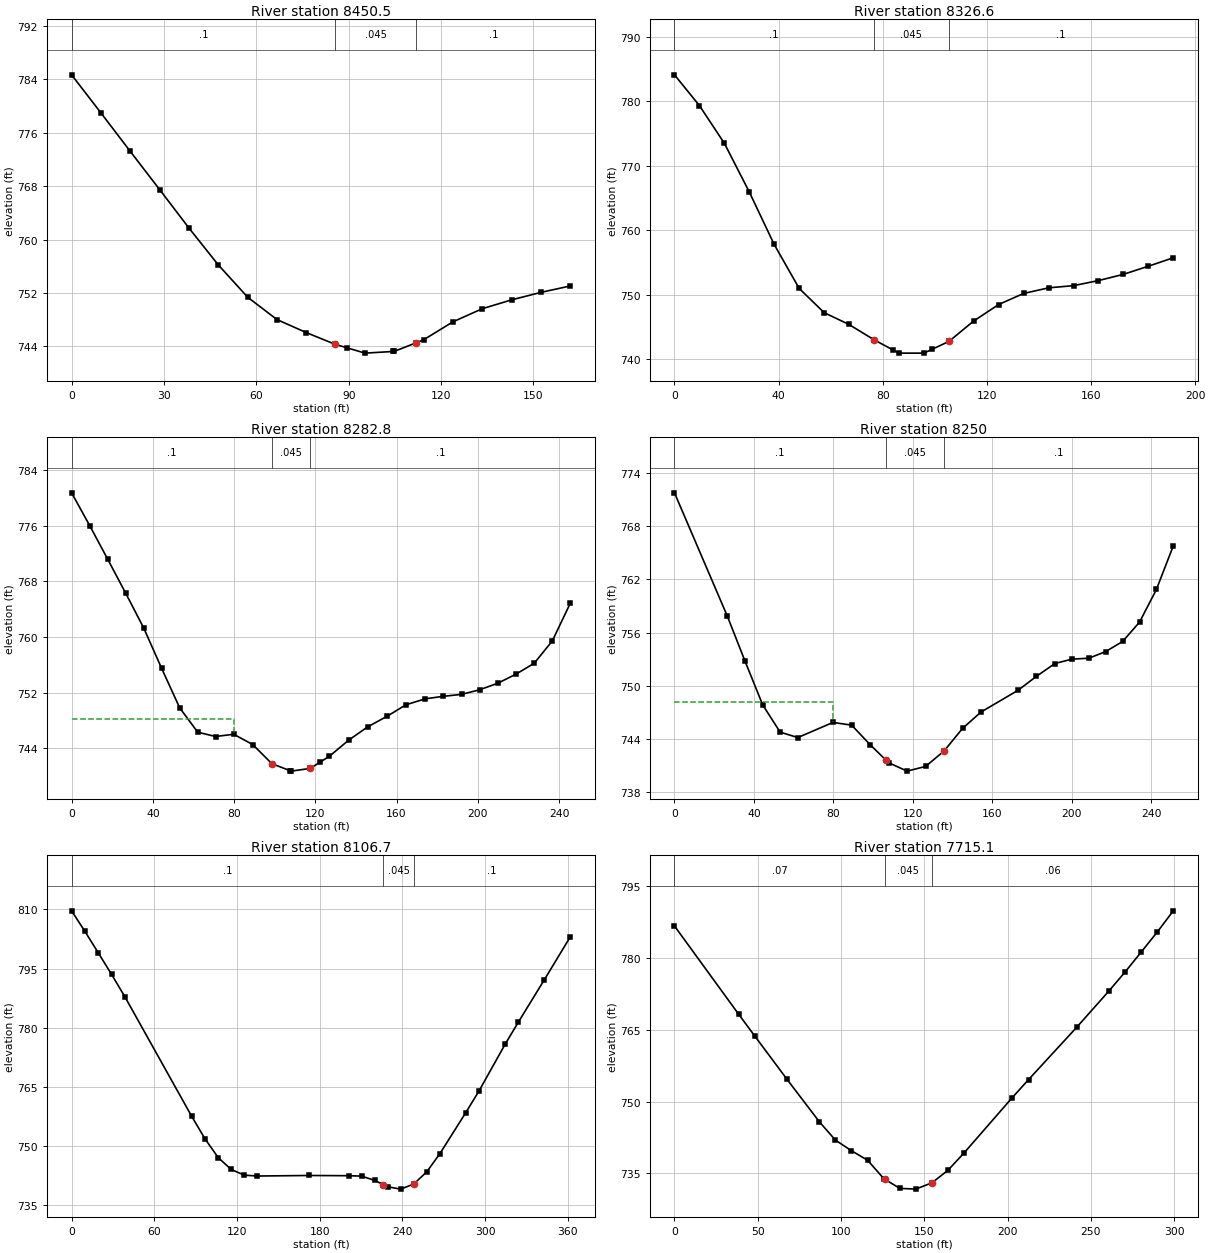
Type RM Length L Ch R = 1 ,8450.5  ,129.1,123.9,118.4
XS GIS Cut Line= 2
      1888130.49      529063.669     1888284.135      529114.884
#Sta/Elev= 21
       0  784.68     9.5  778.99      19  773.24    28.6  767.48    38.1  761.73
    47.6  756.22    57.2  751.35    66.7  748.01    76.2  746.06    85.7  744.28
    89.5  743.77    95.3  742.98   104.5  743.23   104.8  743.24     112744.5511
   114.3  744.97   123.8  747.66   133.4  749.64   142.9  750.96   152.4  752.08
     162  753.05
#Mann= 3 , 0 , 0
       0      .1       0    85.7    .045       0     112      .1       0
Bank Sta=85.7,112
XS Rating Curve= 0 ,0
Exp/Cntr=0.3,0.1

Type RM Length L Ch R = 1 ,8326.6  ,59.4,43.8,28.8
XS GIS Cut Line= 2
     1888105.519      529207.497      1888296.41      529223.646
#Sta/Elev= 24
       0  784.08     9.6   779.3    19.2  773.44    28.7  765.95    38.3  757.78
    47.9  750.97    57.5  747.21      67  745.39    76.5743.0447    76.6  743.02
      84  741.42    86.2  740.94    95.8  740.94      99  741.54   105.4  742.75
   114.9  745.91   124.5  748.47   134.1  750.19   143.7  751.06   153.3   751.4
   162.8  752.18   172.4  753.15     182  754.41   191.6  755.72
#Mann= 3 , 0 , 0
       0      .1       0    76.5    .045       0   105.4      .1       0
Bank Sta=76.5,105.4
XS Rating Curve= 0 ,0
Exp/Cntr=0.3,0.1

Type RM Length L Ch R = 1 ,8282.8  ,32.8,32.9,33.6
XS GIS Cut Line= 4
     1888082.241      529260.305     1888160.612      529275.322
     1888243.675       529230.74     1888315.259      529231.176
#Sta/Elev= 30
       0  780.74     8.9  776.03    17.7  771.23    26.6  766.32    35.5   761.3
    44.3  755.51    53.2  749.82    62.1  746.31    70.9  745.69    79.8  746.01
    89.2  744.53    98.6  741.78   107.5  740.78   108.1  740.71   117.5   741.1
   122.5  742.03   126.9  742.84   136.4  745.16   145.8  747.08   155.2  748.58
   164.6  750.25   174.1  751.11     183  751.47     192  751.75   200.9  752.41
   209.9  753.36   218.8  754.66   227.8  756.23   236.7  759.45   245.6   764.9
#Mann= 3 , 0 , 0
       0      .1       0    98.6    .045       0   117.5      .1       0
#XS Ineff= 2 , 0
           80.13  748.22
Permanent Ineff=
       F       F
Bank Sta=98.6,117.5
XS Rating Curve= 0 ,0
Exp/Cntr=0.3,0.1

Type RM Length L Ch R = 1 ,8250    ,122.8,143.3,162.3
XS GIS Cut Line= 4
     1888071.699      529297.814     1888150.539      529310.485
     1888249.559      529258.863     1888309.158      529257.456
#Sta/Elev= 26
       0  771.78    26.6  757.86    35.5  752.78    44.4  747.84    53.2  744.76
    62.1  744.15    79.8  745.86    89.2  745.55    98.5  743.34   106.4741.6156
   107.8  741.31   117.1  740.36   126.4  740.89   135.7  742.63     145  745.18
   154.3  747.03   172.9  749.48   182.2  751.06   191.5  752.51     200     753
   208.6  753.11   217.1  753.86   225.6     755   234.1  757.18   242.6  760.87
   251.1  765.79
#Mann= 3 , 0 , 0
       0      .1       0   106.4    .045       0   135.7      .1       0
#XS Ineff= 2 , 0
           79.95  748.12
Permanent Ineff=
       F       F
Bank Sta=106.4,135.7
XS Rating Curve= 0 ,0
Exp/Cntr=0.3,0.1

Type RM Length L Ch R = 1 ,8106.7  ,381.2,391.6,401
XS GIS Cut Line= 4
     1887963.256      529319.038     1888039.506      529393.205
     1888202.145      529443.205     1888281.185      529475.583
#Sta/Elev= 27
       0  809.64     9.7  804.41    19.3  799.02      29  793.52    38.7  787.83
      87  757.63    96.7  751.89   106.4  747.07   115.8  744.08   125.3  742.64
   134.7  742.42   172.5  742.56   200.9   742.5   210.4   742.4   219.8  741.32
   226.1740.2457   229.3   739.7   238.7   739.1   248.2  740.38   257.6  743.45
   267.1  748.04     286   758.5   295.5  763.94   314.5   775.8     324  781.36
     343  792.18   361.9   803.1
#Mann= 3 , 0 , 0
       0      .1       0   226.1    .045       0   248.2      .1       0
Bank Sta=226.1,248.2
XS Rating Curve= 0 ,0
Exp/Cntr=0.3,0.1

Type RM Length L Ch R = 1 ,7715.1  ,199.2,186.3,172.9
XS GIS Cut Line= 2
     1887765.272      529569.102     1887987.494      529769.796
#Sta/Elev= 23
       0  786.72    38.6  768.22    48.3  763.65    67.6  754.62    86.9  745.79
    96.6  741.93   106.2  739.72   115.9  737.72   125.6  733.89   126.2733.7618
   135.2  731.84   144.9  731.68   154.6  733.02   164.2  735.64   173.9  739.29
   202.8  750.84   212.5  754.58   241.5  765.56   260.8  773.14   270.5  777.11
   280.1  781.25   289.8  785.47   299.4  789.89
#Mann= 3 , 0 , 0
       0     .07       0   126.2    .045       0   154.6     .06       0
Bank Sta=126.2,154.6
XS Rating Curve= 0 ,0
Exp/Cntr=0.3,0.1

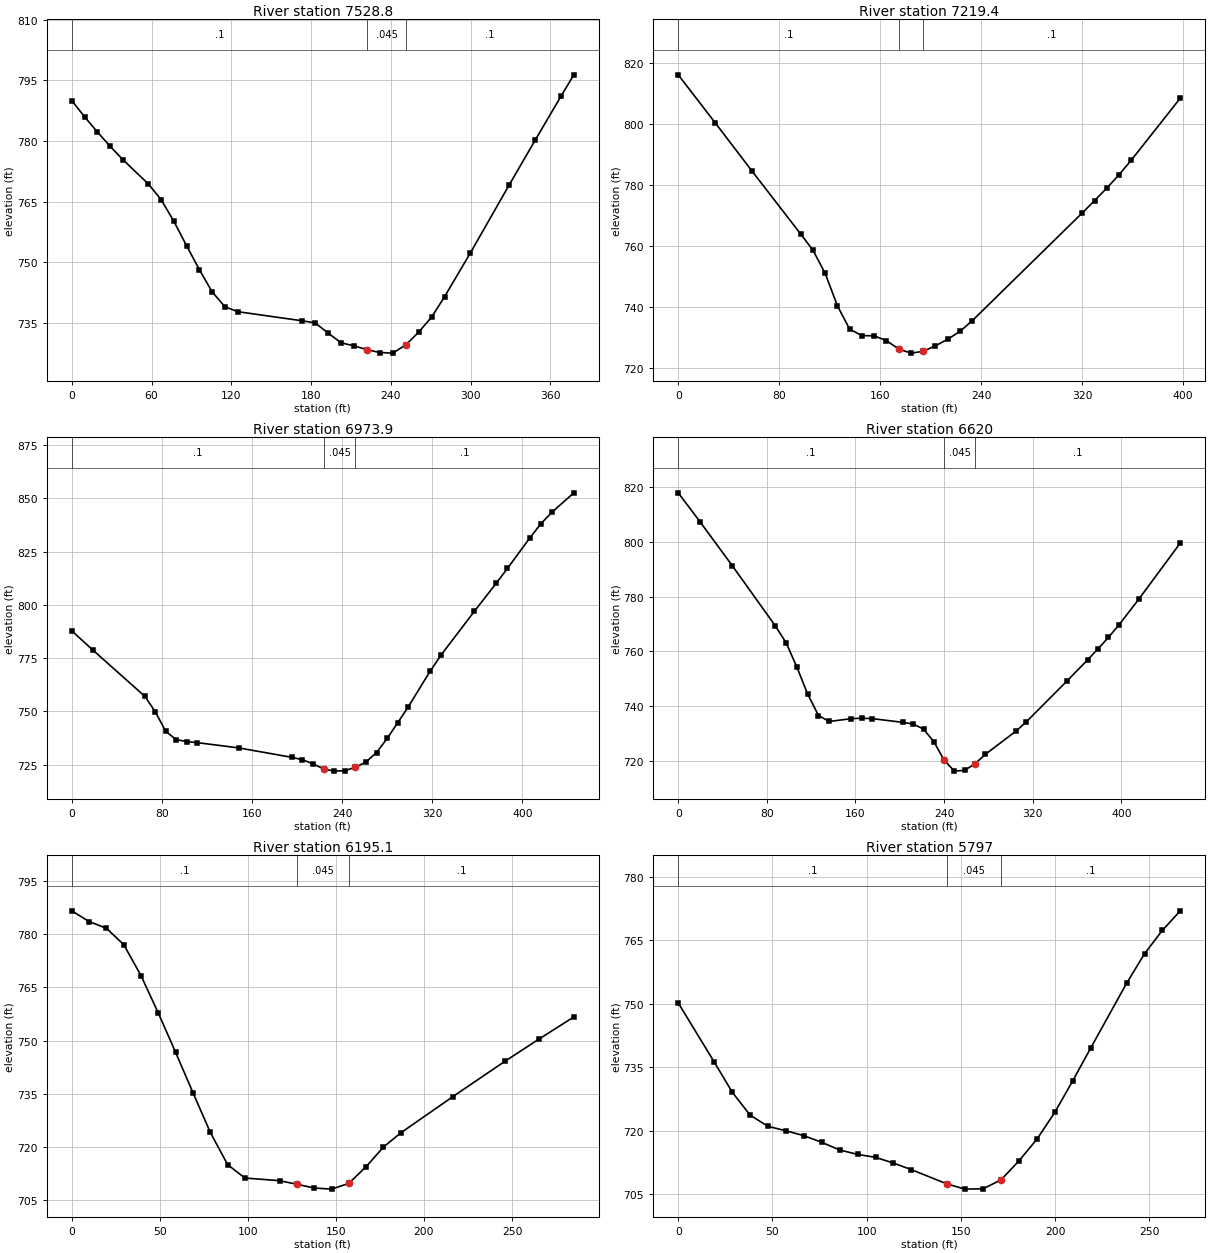
Type RM Length L Ch R = 1 ,7528.8  ,316.1,309.5,302.4
XS GIS Cut Line= 3
     1887573.975      529805.977     1887707.588      529820.783
     1887947.943      529858.355
#Sta/Elev= 30
       0     790     9.6  786.02    19.2  782.26    28.8  778.71    38.4   775.4
    57.6  769.37    67.2   765.5    76.8  760.13    86.4  754.07      96  748.15
   105.6  742.66   115.2  738.99   124.8  737.76   173.4   735.5   183.1  734.98
   192.8  732.47   202.6  730.06   212.3   729.3     222  728.37   231.7  727.65
   241.5   727.5   251.5729.5984   260.9  732.68   270.7  736.41   280.4  741.44
   299.9  752.32     329   769.1   348.5  780.14     368  791.07   377.7  796.38
#Mann= 3 , 0 , 0
       0      .1       0     222    .045       0   251.5      .1       0
Bank Sta=222,251.5
XS Rating Curve= 0 ,0
Exp/Cntr=0.3,0.1

Type RM Length L Ch R = 1 ,7219.4  ,242.7,245.5,248
XS GIS Cut Line= 2
     1887581.184      530168.761     1887974.517      530109.872
#Sta/Elev= 24
       0  816.25    29.1  800.57    58.2  784.73      97   763.9   106.7   758.6
   116.4  750.95   126.1  740.29   135.8   732.6   145.5  730.52   155.2  730.42
   164.9  728.86   174.6   726.1   184.3  724.74     194  725.33   203.7  727.15
   213.4  729.29   223.1  731.87   232.8  735.36   320.1  770.87   329.8   774.9
   339.5  779.03   349.2   783.4   358.9  788.21   397.7  808.59
#Mann= 3 , 0 , 0
       0      .1       0   174.6    .045       0     194      .1       0
Bank Sta=174.6,194
XS Rating Curve= 0 ,0
Exp/Cntr=0.3,0.1

Type RM Length L Ch R = 1 ,6973.9  ,315.2,353.9,391.9
XS GIS Cut Line= 4
     1887600.454      530295.358     1887719.204      530384.247
     1887878.927      530379.386     1888008.788      530424.525
#Sta/Elev= 30
       0  787.85    18.5  778.93    64.9   757.1    74.2  749.76    83.4  740.68
    92.7   736.8     102  735.87   111.2  735.39   148.3  732.89   195.3  728.48
   204.7  727.36   214.1  725.43   223.5  723.05   232.9     722   242.3  722.22
   251.7  723.79   261.1  726.29   270.5  730.72   279.9  737.35   289.3   744.7
   298.7  752.24     318  768.84   327.8  776.54   357.2  796.94   376.9  810.32
   386.7  817.18   406.3  831.31   416.2  838.02     426  843.45   445.6  852.64
#Mann= 3 , 0 , 0
       0      .1       0   223.5    .045       0   251.7      .1       0
Bank Sta=223.5,251.7
XS Rating Curve= 0 ,0
Exp/Cntr=0.3,0.1

Type RM Length L Ch R = 1 ,6620    ,457.7,424.9,391.5
XS GIS Cut Line= 4
     1887456.552      530354.208     1887580.281      530478.344
     1887568.362      530607.294     1887658.871      530724.981
#Sta/Elev= 30
       0  817.86    19.5  807.39    48.7  791.33    87.6  769.34    97.4  763.14
   107.1   754.3   116.8  744.46   126.6  736.63   136.3  734.45   155.8  735.46
   165.5  735.66   175.3  735.48     203  734.12   212.3   733.5   221.5  731.64
   230.8  727.02     240  720.37   249.3  716.34   258.5  716.64   267.8  718.97
     277  722.41   304.8  730.91     314  734.25   351.2  749.33   369.7     757
     379  761.01   388.3  765.11   397.6  769.56   416.1  779.27   453.2  799.56
#Mann= 3 , 0 , 0
       0      .1       0     240    .045       0   267.8      .1       0
Bank Sta=240,267.8
XS Rating Curve= 0 ,0
Exp/Cntr=0.3,0.1

Type RM Length L Ch R = 1 ,6195.1  ,393.7,398.1,401.9
XS GIS Cut Line= 2
     1887170.738      530789.363     1887450.182       530846.03
#Sta/Elev= 23
       0  786.61     9.8   783.6    19.7  781.67    29.5  777.09    39.3  768.36
    49.2  757.73      59  746.68    68.8  735.37    78.7  724.13    88.5  715.06
    98.3  711.29     118  710.54   127.8  709.54   137.6  708.48   147.5  708.16
   157.3  709.78   167.2  714.52     177  720.02   186.8  724.01   216.3   734.2
   245.8  744.14   265.5  750.52   285.1  756.69
#Mann= 3 , 0 , 0
       0      .1       0   127.8    .045       0   157.3      .1       0
Bank Sta=127.8,157.3
XS Rating Curve= 0 ,0
Exp/Cntr=0.3,0.1

Type RM Length L Ch R = 1 ,5797    ,206.2,209.7,213.2
XS GIS Cut Line= 2
     1887065.981      531143.217     1887313.203      531242.523
#Sta/Elev= 26
       0  750.18      19  736.31    28.6  729.15    38.1   723.7    47.6  721.05
    57.1     720    66.6  718.85    76.1  717.28    85.6  715.47    95.2  714.42
   104.7  713.72   114.2  712.37   123.7  710.82   142.8707.4172   152.2  706.22
   161.8   706.3   171.3  708.42   180.8   712.9   190.3     718   199.8  724.34
   209.3  731.78   218.8  739.49   237.9  754.82   247.4  761.79   256.9  767.33
   266.4  771.93
#Mann= 3 , 0 , 0
       0      .1       0   142.8    .045       0   171.3      .1       0
Bank Sta=142.8,171.3
XS Rating Curve= 0 ,0
Exp/Cntr=0.3,0.1

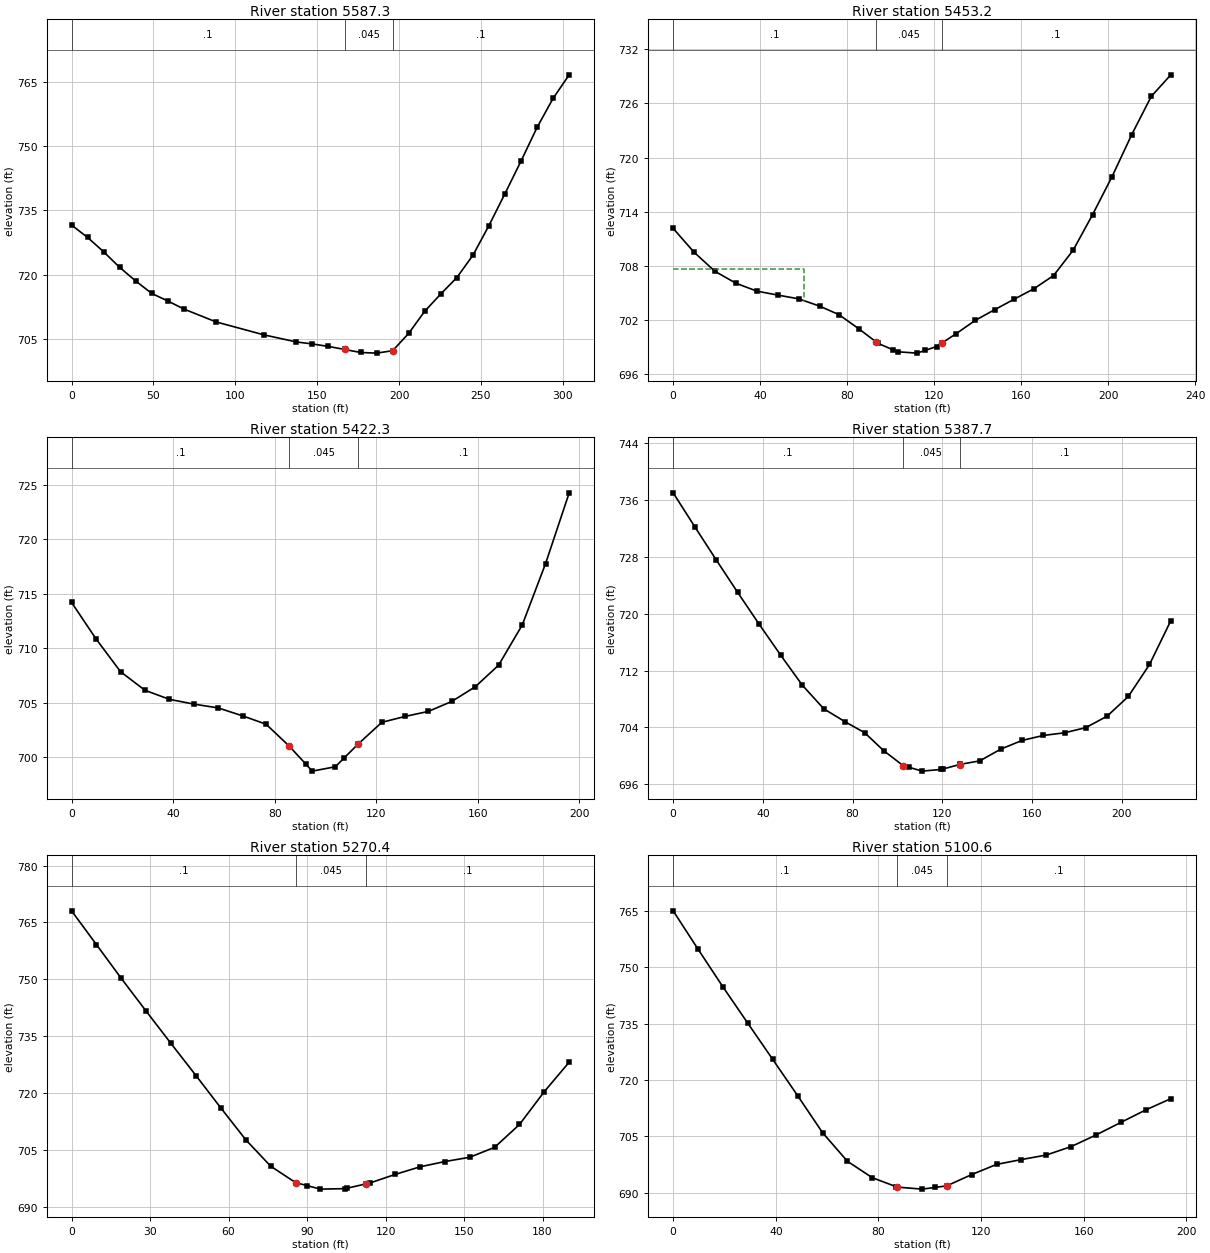
Type RM Length L Ch R = 1 ,5587.3  ,112.2,134,155.9
XS GIS Cut Line= 2
     1886947.231      531287.662     1887208.342      531443.217
#Sta/Elev= 28
       0  731.58     9.8   728.7    19.6  725.35    29.4  721.71    39.2  718.53
      49  715.62    58.8  713.87    68.6  711.99    88.2  708.99   117.6  705.95
   137.3  704.31   147.1  703.84   156.9  703.26   166.7  702.56   176.5  701.85
   186.3   701.7   196.1  702.27   205.9  706.32   215.7  711.49   225.5  715.51
   235.3  719.34   245.1  724.54   254.9  731.48   264.7  738.94   274.5  746.54
   284.3  754.39   294.1  761.18   303.9  766.65
#Mann= 3 , 0 , 0
       0      .1       0   166.7    .045       0   196.1      .1       0
Bank Sta=166.7,196.1
XS Rating Curve= 0 ,0
Exp/Cntr=0.3,0.1

Type RM Length L Ch R = 1 ,5453.2  ,15.8,31,45.7
XS GIS Cut Line= 4
     1886977.648      531355.806     1887005.801      531417.031
     1887010.946      531497.413       1887008.6      531578.219
#Sta/Elev= 30
       0  712.14     9.6   709.5    19.2  707.38    28.9  706.05    38.5  705.18
    48.1  704.74    57.8  704.32    67.4  703.51    76.3  702.56    85.3  701.01
    93.4699.5266    94.2  699.38   100.9  698.69   103.2  698.45   112.1   698.3
   115.9  698.61   121.1  699.03   123.4699.3944     130  700.44     139  701.95
   147.9  703.13   156.9   704.3   165.9  705.45   174.9  706.91   183.9  709.72
   192.8  713.65   201.8  717.89   210.8  722.53   219.8  726.78   228.8  729.18
#Mann= 3 , 0 , 0
       0      .1       0    93.4    .045       0   123.4      .1       0
#XS Ineff= 2 , 0
              60  707.68
Permanent Ineff=
       F       F
Bank Sta=93.4,123.4
XS Rating Curve= 0 ,0
Exp/Cntr=0.3,0.1

Type RM Length L Ch R = 1 ,5422.3  ,34.5,34.6,33.6
XS GIS Cut Line= 4
     1886968.983      531359.726     1886996.724      531421.193
     1886961.777      531474.623       1886964.7      531539.235
#Sta/Elev= 24
       0   714.2     9.6  710.87    19.3  707.85    28.9  706.15    38.5  705.32
    48.2  704.88    57.8  704.53    67.4   703.8    76.6  703.04    85.7  701.04
    92.2   699.4    94.8  698.74   103.9  699.14   107.2  699.91     113  701.25
   122.2  703.21   131.3  703.75   140.5  704.21   149.8  705.13     159  706.47
   168.2  708.45   177.5  712.13   186.7  717.76     196  724.24
#Mann= 3 , 0 , 0
       0      .1       0    85.7    .045       0     113      .1       0
Bank Sta=85.7,113
XS Rating Curve= 0 ,0
Exp/Cntr=0.3,0.1

Type RM Length L Ch R = 1 ,5387.7  ,156.6,117.3,77.9
XS GIS Cut Line= 4
     1886925.928       531341.67     1886966.125      531407.119
     1886933.358      531457.216     1886953.521      531540.011
#Sta/Elev= 28
       0  737.01     9.6  732.26    19.2  727.58    28.8  722.99    38.4   718.5
      48  714.15    57.6  709.95    67.2  706.62    76.8  704.78    85.4  703.26
    93.9  700.73   102.5  698.65   105.2   698.4     111  697.86   119.6   698.1
   120.2  698.15   127.7698.7861   128.1  698.82   136.7   699.3   146.1  700.96
   155.6  702.18   165.1  702.88   174.5  703.25     184  703.98   193.5  705.59
     203  708.38   212.4  712.86   221.9  719.02
#Mann= 3 , 0 , 0
       0      .1       0   102.5    .045       0   127.7      .1       0
Bank Sta=102.5,127.7
XS Rating Curve= 0 ,0
Exp/Cntr=0.3,0.1

Type RM Length L Ch R = 1 ,5270.4  ,174.1,169.8,165.4
XS GIS Cut Line= 2
     1886781.039      531479.317      1886954.65      531557.094
#Sta/Elev= 24
       0  768.07     9.5  759.18      19  750.27    28.5  741.64      38  733.12
    47.6  724.61    57.1  716.08    66.6  707.72    76.1  700.77    85.6  696.45
    90.1  695.63    95.1  694.72   104.6  694.85   105.1  694.93   112.6696.1133
   114.1  696.35   123.6  698.58   133.2   700.6   142.7  701.99   152.2  703.12
   161.7  705.74   171.2  711.76   180.7  720.43   190.2  728.19
#Mann= 3 , 0 , 0
       0      .1       0    85.6    .045       0   112.6      .1       0
Bank Sta=85.6,112.6
XS Rating Curve= 0 ,0
Exp/Cntr=0.3,0.1

Type RM Length L Ch R = 1 ,5100.6  ,177.4,163.4,148.8
XS GIS Cut Line= 2
     1886723.782      531658.261     1886912.684      531702.028
#Sta/Elev= 23
       0     765     9.7  754.79    19.4  744.75    29.1  735.07    38.8  725.45
    48.5   715.8    58.2  705.96    67.9  698.33    77.6  693.96      87  691.54
    87.3  691.46      97  690.92     102  691.37   106.6  691.79   116.3  694.79
     126   697.5   135.7  698.79   145.4     700   155.1  702.25   164.8  705.34
   174.5   708.7   184.2  712.02   193.9     715
#Mann= 3 , 0 , 0
       0      .1       0    87.3    .045       0   106.6      .1       0
Bank Sta=87.3,106.6
XS Rating Curve= 0 ,0
Exp/Cntr=0.3,0.1

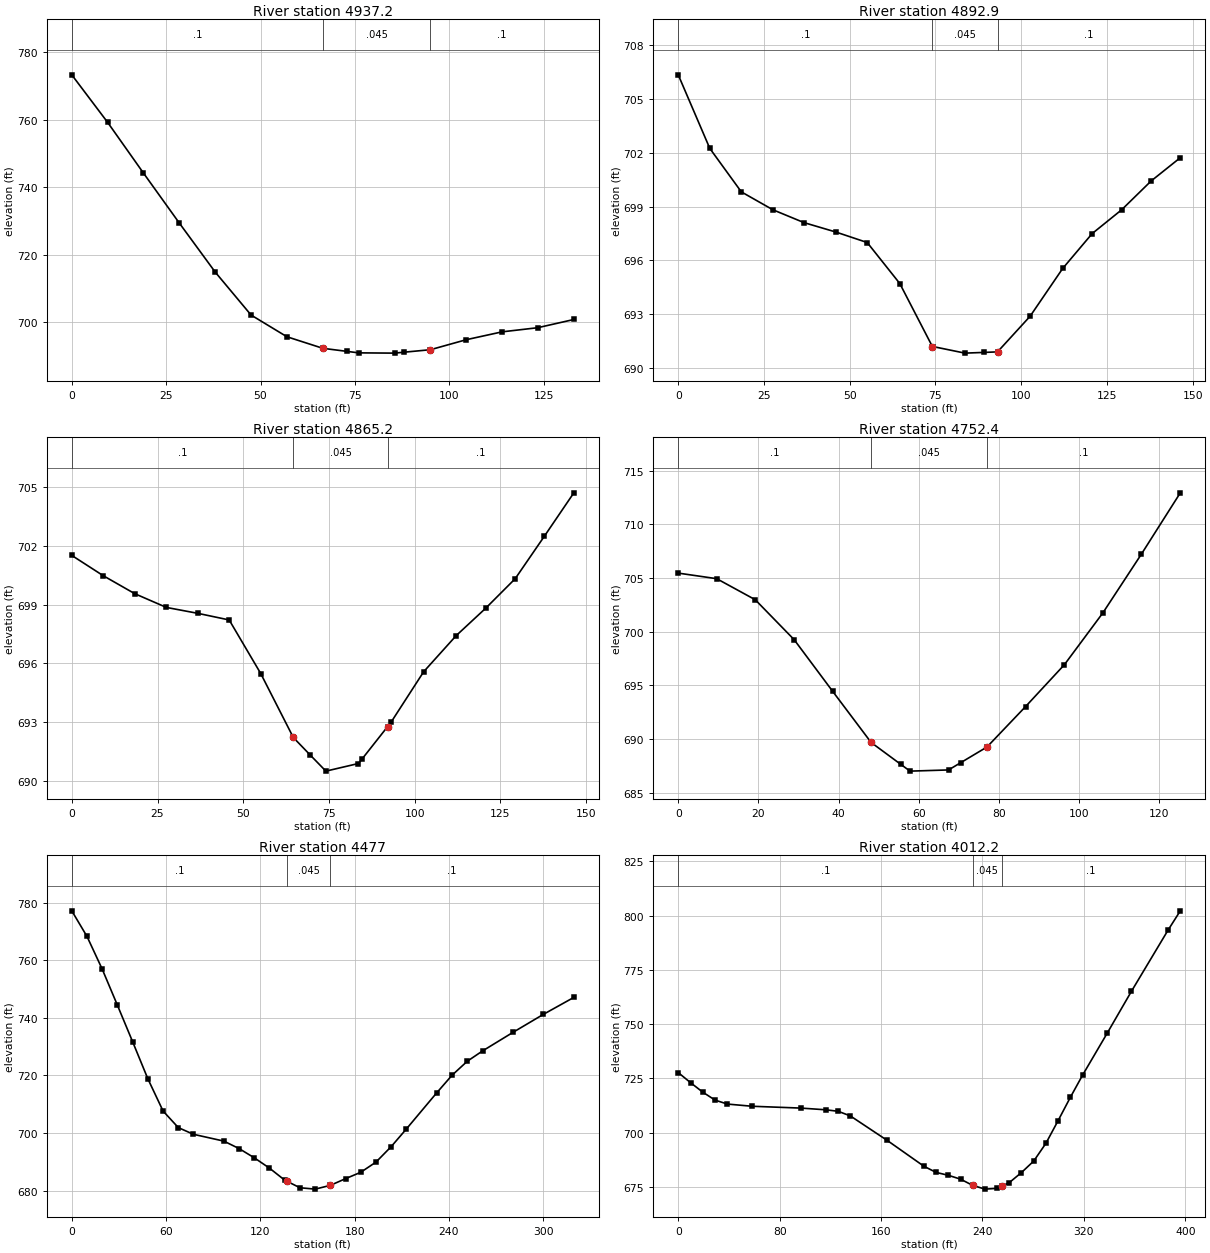
Type RM Length L Ch R = 1 ,4937.2  ,68.4,44.3,19.3
XS GIS Cut Line= 2
      1886746.69      531871.915     1886868.883      531819.527
#Sta/Elev= 17
       0   773.3     9.5  759.21      19  744.16    28.5  729.34      38  714.82
    47.5  702.09      57  695.65    66.5  692.23    72.9  691.32      76  690.88
    85.5   690.8    87.9  691.06      95  691.81   104.5  694.78     114  697.11
   123.4  698.33     133  700.77
#Mann= 3 , 0 , 0
       0      .1       0    66.5    .045       0      95      .1       0
Bank Sta=66.5,95
XS Rating Curve= 0 ,0
Exp/Cntr=0.3,0.1

Type RM Length L Ch R = 1 ,4892.9  ,27.3,27.7,28.5
XS GIS Cut Line= 4
     1886822.223      531949.504     1886844.767      531899.215
     1886851.125      531842.567     1886874.488      531817.425
#Sta/Elev= 19
       0  706.36     9.2  702.25    18.4  699.82    27.6  698.82    36.7   698.1
    45.9  697.58    55.1  696.99    64.6   694.7    74.1  691.18    74.2  691.18
    83.6  690.81    89.2  690.85    93.1  690.88   102.6  692.87   112.1  695.54
   120.7  697.49   129.3  698.82   137.9  700.43   146.4  701.73
#Mann= 3 , 0 , 0
       0      .1       0    74.1    .045       0    93.1      .1       0
Bank Sta=74.1,93.1
XS Rating Curve= 0 ,0
Exp/Cntr=0.3,0.1

Type RM Length L Ch R = 1 ,4865.2  ,89.3,112.8,136.4
XS GIS Cut Line= 4
     1886849.195      531952.938     1886871.738      531902.648
     1886878.097         531846.     1886898.253      531818.269
#Sta/Elev= 20
       0  701.52     9.2  700.48    18.4  699.56    27.6  698.86    36.7  698.56
    45.9  698.22    55.1  695.48    64.6  692.21    69.6   691.3    74.1  690.49
    83.6  690.88    84.6   691.1    92.1692.7676    93.1  692.99   102.6  695.57
   112.1  697.42   120.7  698.82   129.3  700.33   137.8   702.5   146.4  704.72
#Mann= 3 , 0 , 0
       0      .1       0    64.6    .045       0    92.1      .1       0
Bank Sta=64.6,92.1
XS Rating Curve= 0 ,0
Exp/Cntr=0.3,0.1

Type RM Length L Ch R = 1 ,4752.4  ,280.4,275.4,270.2
XS GIS Cut Line= 2
     1886879.108      531998.154      1886993.44      531947.239
#Sta/Elev= 17
       0  705.46     9.6  704.94    19.2  702.98    28.9  699.26    38.5  694.45
      48689.7297    48.1  689.68    55.5  687.64    57.8  687.01    67.4  687.12
    70.5  687.81      77  689.26    86.6  693.02    96.3  696.93   105.9  701.76
   115.5  707.23   125.2  712.94
#Mann= 3 , 0 , 0
       0      .1       0      48    .045       0      77      .1       0
Bank Sta=48,77
XS Rating Curve= 0 ,0
Exp/Cntr=0.3,0.1

Type RM Length L Ch R = 1 ,4477    ,468.3,464.8,461
XS GIS Cut Line= 2
     1886878.995      532327.713     1887134.377      532135.785
#Sta/Elev= 30
       0  777.17     9.7  768.27    19.4  756.89      29  744.46    38.7  731.75
    48.4  718.87    58.1  707.66    67.8   701.9    77.4  699.58    96.8  697.21
   106.5  694.61   116.2   691.4   125.8  687.83   135.5  683.66   136.8683.3054
   145.2  681.02   154.9  680.54   164.6  681.86   174.2  684.17   183.9  686.39
   193.6  689.93   203.3  695.32     213  701.47   232.3  714.02     242  720.09
   251.7  724.95   261.4  728.52   280.7  734.95   300.1  741.22   319.5  747.11
#Mann= 3 , 0 , 0
       0      .1       0   136.8    .045       0   164.6      .1       0
Bank Sta=136.8,164.6
XS Rating Curve= 0 ,0
Exp/Cntr=0.3,0.1

Type RM Length L Ch R = 1 ,4012.2  ,218.1,243.4,267.8
XS GIS Cut Line= 3
      1887165.28      532630.924     1887311.111      532577.654
      1887477.78      532403.841
#Sta/Elev= 30
       0  727.65     9.7  723.01    19.4  718.61    29.1  714.95    38.8  713.14
    58.2  712.13      97  711.28   116.4   710.5   126.2  709.81   135.8  707.67
   164.9  696.38   193.8   684.5   203.4  681.66     213  680.33   222.7  678.55
   232.3  675.68     242  673.95   251.6  674.31   255.5675.3866   261.2  676.96
   270.8   681.6   280.5  686.91   290.1  695.09   299.7  705.52   309.4   716.3
     319  726.47   338.3  745.68   357.5  765.05   386.4  793.25   396.1  802.17
#Mann= 3 , 0 , 0
       0      .1       0   232.3    .045       0   255.5      .1       0
Bank Sta=232.3,255.5
XS Rating Curve= 0 ,0
Exp/Cntr=0.3,0.1