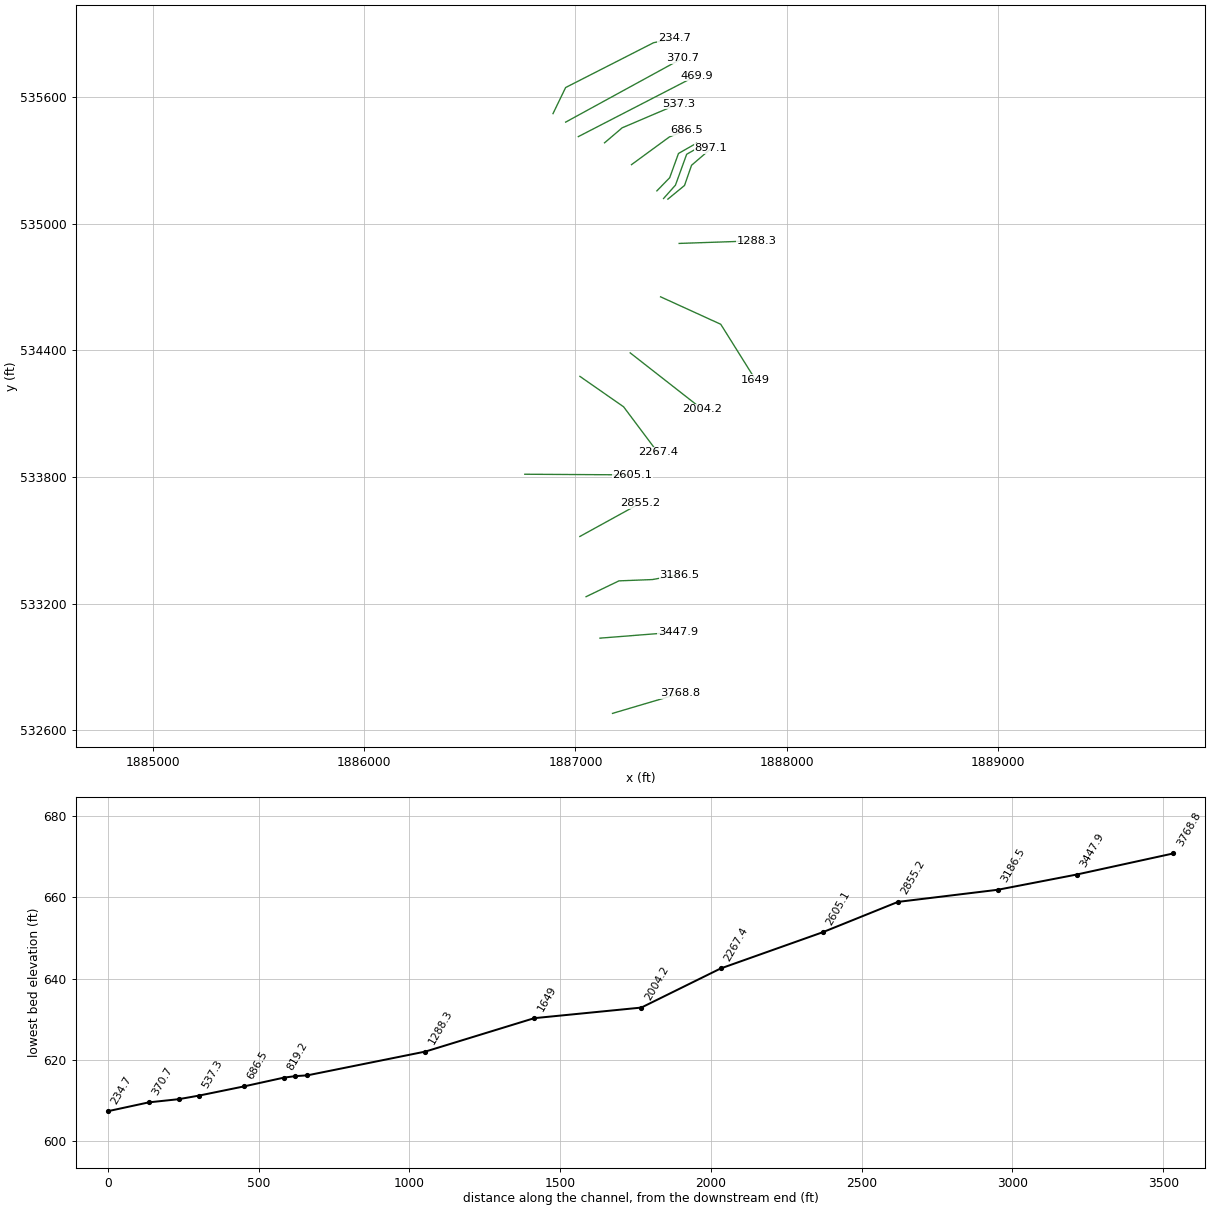
HEC-RAS study QUENSHLSCK.prj: QUENSHLSCK

--- QUENSHLSCK.g01 (geometry) --- (continued)

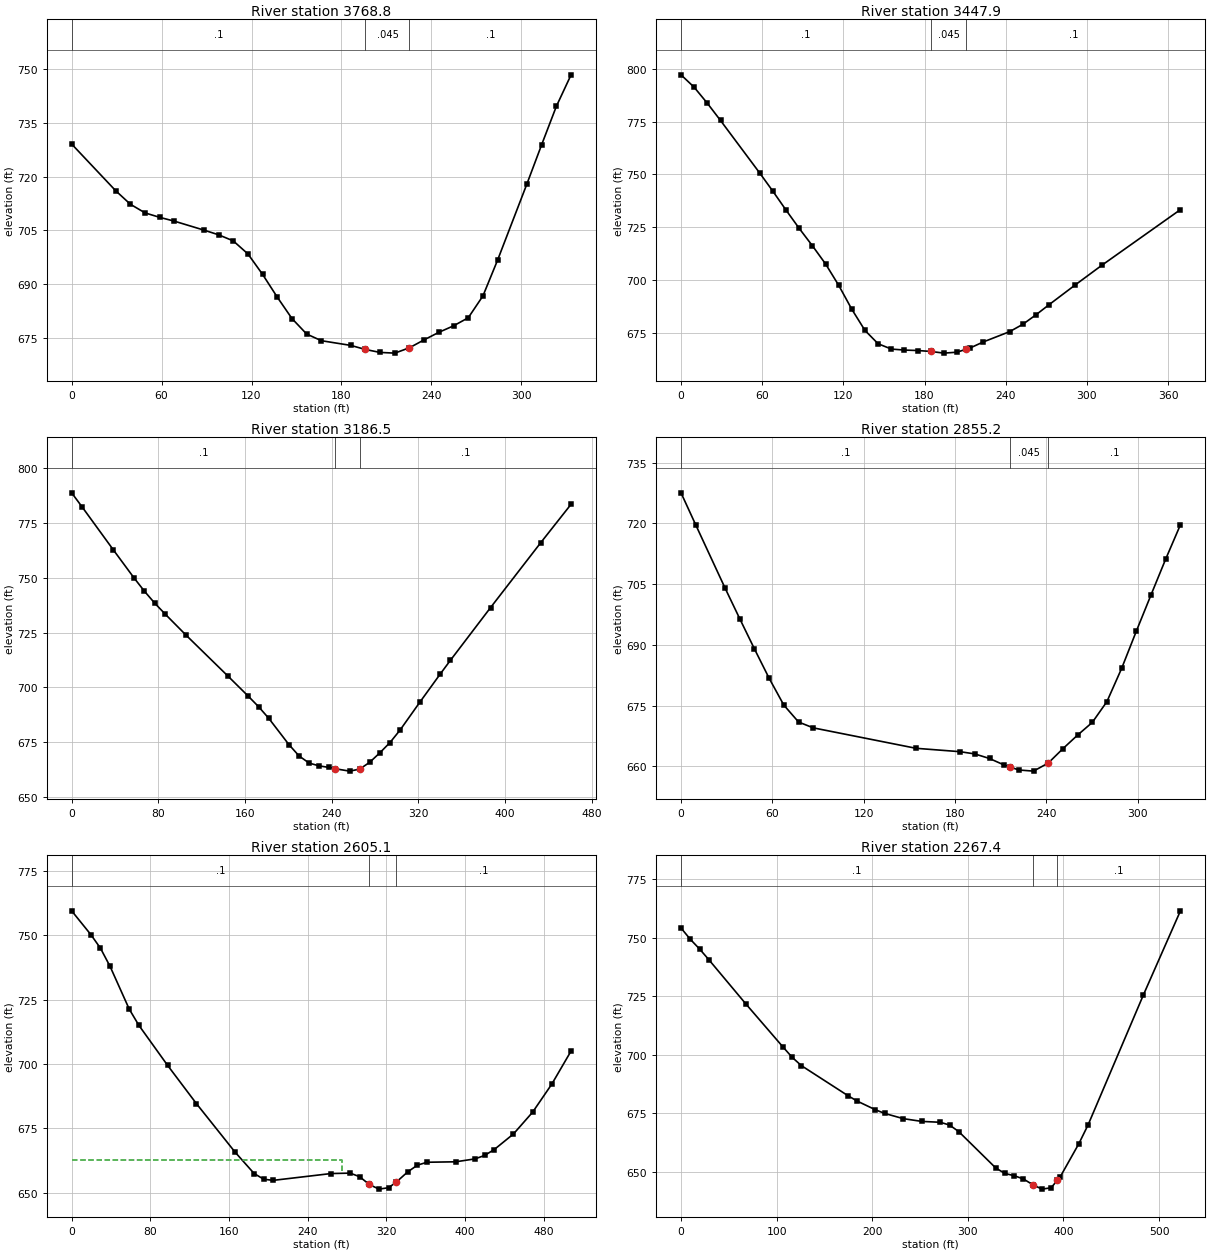
Type RM Length L Ch R = 1 ,3768.8  ,325.3,320.9,315.9
XS GIS Cut Line= 2
     1887175.176      532679.188      1887494.62      532773.806
#Sta/Elev= 30
       0   729.1    29.4  716.06    39.2  712.29      49  709.87    58.8  708.63
    68.6  707.56    88.2  705.08      98  703.77   107.8  702.07   117.6  698.43
   127.4  692.71   137.2  686.35     147  680.38   156.8  676.06   166.6   674.2
   186.2  672.89     196  671.75   205.7  670.93   215.6  670.73   225.4  672.23
   235.2  674.45     245  676.54   254.8  678.35   264.6   680.6   274.4   686.7
   284.2  696.72   303.8  718.03   313.6  728.94   323.4  739.64   333.2  748.42
#Mann= 3 , 0 , 0
       0      .1       0     196    .045       0   225.4      .1       0
Bank Sta=196,225.4
XS Rating Curve= 0 ,0
Exp/Cntr=0.3,0.1

Type RM Length L Ch R = 1 ,3447.9  ,262.2,261.4,260.4
XS GIS Cut Line= 2
     1887115.974      533035.785      1887484.03      533064.952
#Sta/Elev= 30
       0  797.07     9.7  791.22    19.4  783.69    29.2   775.5    58.3  750.56
      68  741.98    77.7  733.08    87.4  724.47    97.2  716.22   106.9  707.66
   116.6  697.56   126.3  686.22     136  676.26   145.7  669.97   155.5  667.46
   165.2  666.98   174.9  666.78   184.6  666.34   194.3  665.54     204  665.98
   210.8667.3817   213.8     668   223.5  670.84   242.9  675.68   252.6  679.13
   262.3   683.6     272  688.39   291.5  697.81   310.9  706.97   369.2  733.37
#Mann= 3 , 0 , 0
       0      .1       0   184.6    .045       0   210.8      .1       0
Bank Sta=184.6,210.8
XS Rating Curve= 0 ,0
Exp/Cntr=0.3,0.1

Type RM Length L Ch R = 1 ,3186.5  ,320.7,331.3,341.6
XS GIS Cut Line= 4
     1887050.002      533232.313     1887205.557      533307.313
     1887363.891      533313.563     1887491.669      533337.174
#Sta/Elev= 30
       0  788.77     9.6  782.38    38.4  762.81    57.6  749.95    67.2  743.89
    76.8  738.38    86.4  733.43   105.5   723.9   143.9  705.36   163.1  695.98
   172.7  691.14     182  685.89   200.6  673.91     210  668.71   219.3  665.46
   228.6  664.19   237.9  663.46   243.5662.8821   256.6   661.8   265.9   662.7
   275.2  665.84   284.5  670.12   293.9  674.83   303.2  680.52   321.8  693.47
   340.4  706.17   349.7  712.36   386.8  736.44   433.2  766.09   461.1  783.55
#Mann= 3 , 0 , 0
       0      .1       0   243.5    .045       0   265.9      .1       0
Bank Sta=243.5,265.9
XS Rating Curve= 0 ,0
Exp/Cntr=0.3,0.1

Type RM Length L Ch R = 1 ,2855.2  ,262,250.1,237.8
XS GIS Cut Line= 2
     1887020.798      533517.915      1887308.02      533676.248
#Sta/Elev= 27
       0  727.55     9.6  719.69    28.9  704.05    38.6  696.44    48.2  689.02
    57.9  681.74    67.5  675.14    77.2  670.95    86.8  669.51   154.3  664.46
   183.3  663.62   192.9  663.07   202.6  661.94   212.2  660.33   216.3659.8101
   221.9   659.1   231.5  658.82   241.2  660.82   250.8  664.36   260.4   667.7
   270.1  670.85   279.7  675.98   289.4  684.21     299  693.36   308.7  702.37
   318.3  711.18     328  719.67
#Mann= 3 , 0 , 0
       0      .1       0   216.3    .045       0   241.2      .1       0
Bank Sta=216.3,241.2
XS Rating Curve= 0 ,0
Exp/Cntr=0.3,0.1

Type RM Length L Ch R = 1 ,2605.1  ,358.2,337.7,316.3
XS GIS Cut Line= 2
     1886760.114      533812.803     1887268.066       533809.78
#Sta/Elev= 30
       0  759.47    19.5  750.25    29.3  744.96    39.1  737.87    58.6  721.27
    68.4  714.98    97.7  699.38     127  684.53   166.1  665.79   185.6  657.42
   195.4  655.19   205.1  654.76   263.8   657.4   283.3  657.57     293  656.16
   302.8  653.15   312.6  651.35   322.4   651.9   330.2654.0784   341.9  658.07
   351.7  660.66   361.4  661.79   390.7  661.97   410.3   663.1     420  664.43
   429.8  666.71   449.4  672.78   468.9  681.25   488.4  692.15     508     705
#Mann= 3 , 0 , 0
       0      .1       0   302.8    .045       0   330.2      .1       0
#XS Ineff= 2 , 0
          274.73  662.54
Permanent Ineff=
       F       F
Bank Sta=302.8,330.2
XS Rating Curve= 0 ,0
Exp/Cntr=0.3,0.1

Type RM Length L Ch R = 1 ,2267.4  ,257,263.2,269.1
XS GIS Cut Line= 3
     1887020.902      534276.679       1887227.5      534132.582
     1887389.483      533915.945
#Sta/Elev= 30
       0   754.1     9.7  749.29    19.4  745.14    29.1  740.56    67.8  721.66
   106.6  703.27   116.2  698.84   125.9  695.27   174.4  682.48   184.1  680.14
   203.4  676.39   213.1  674.83   232.5   672.6   251.9  671.42   271.2  671.05
   280.9  669.87   290.5  667.07   329.2  651.52   338.8  649.16   348.5  648.22
   358.2   646.8   367.8   644.4   377.5  642.47   387.1  643.04   393.5646.2004
   396.8  647.83   416.1  661.87   425.8  669.94   483.7  725.55   522.4  761.45
#Mann= 3 , 0 , 0
       0      .1       0   367.8    .045       0   393.5      .1       0
Bank Sta=367.8,393.5
XS Rating Curve= 0 ,0
Exp/Cntr=0.3,0.1

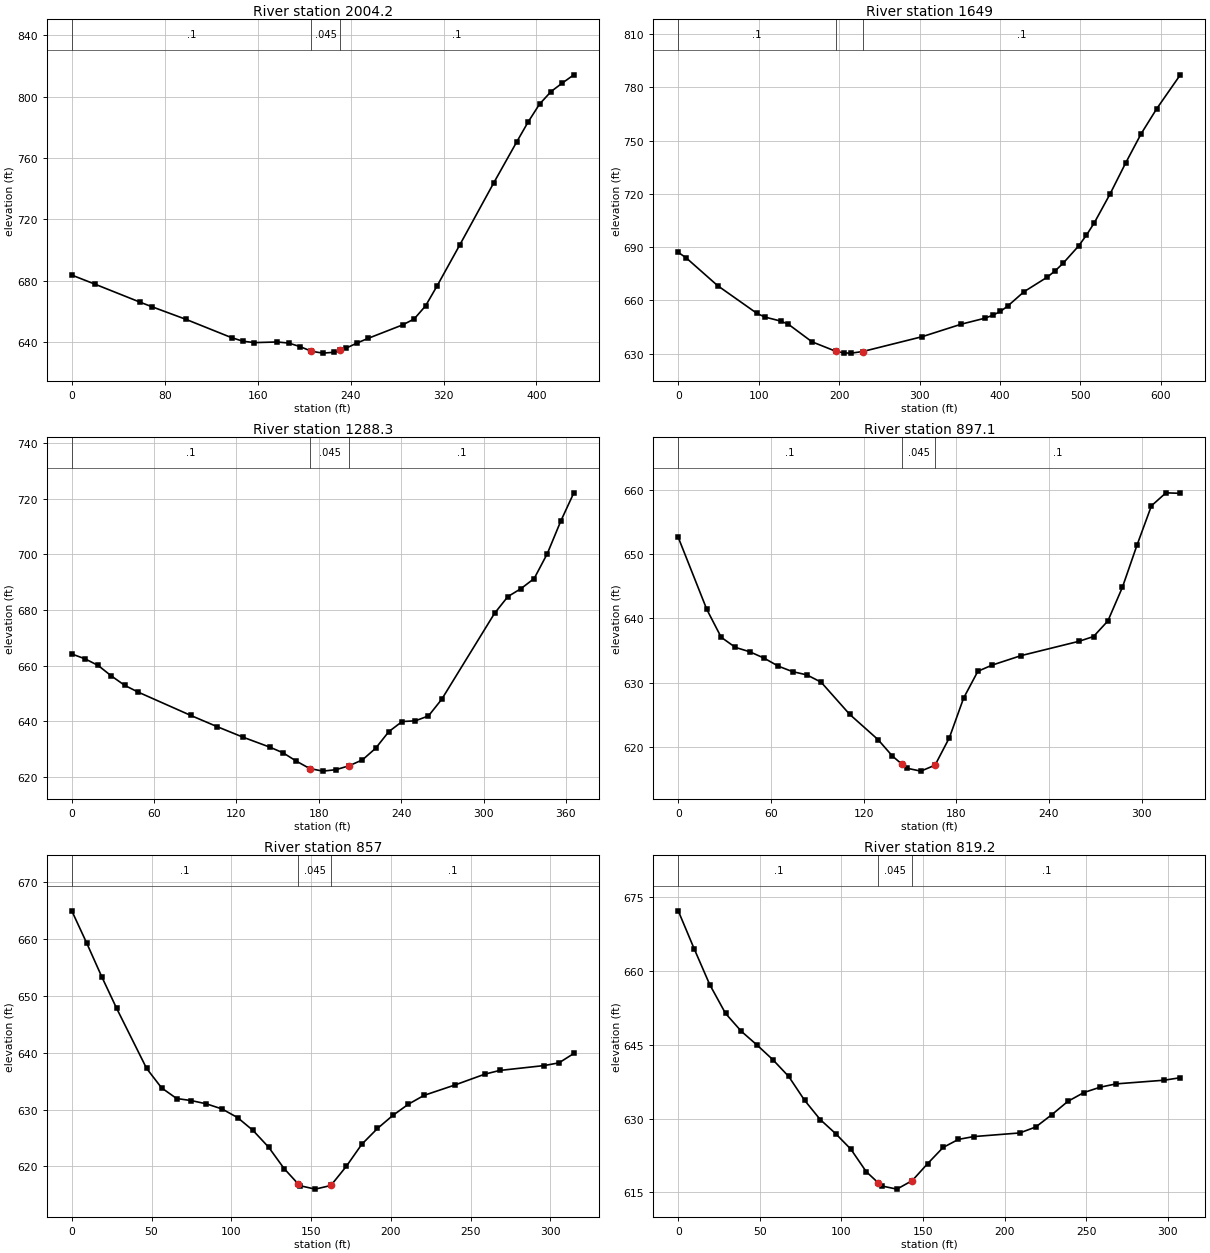
Type RM Length L Ch R = 1 ,2004.2  ,349.6,355.1,360.2
XS GIS Cut Line= 2
     1887258.772      534388.141     1887598.955      534121.562
#Sta/Elev= 30
       0  683.71    19.6  677.89    58.9  666.02    68.8  663.13    98.2  654.89
   137.5  642.96   147.3  640.62   157.2  639.71   176.8  640.12   186.6  639.44
   196.4  637.14   206.3  634.08   216.1  632.86   225.9  633.42     231634.7262
   235.7  635.93   245.6  639.46   255.4  642.57   284.8  651.25   294.7  655.09
   304.5  663.58   314.3   676.4     334  703.34   363.4  743.98   383.1  770.56
   392.9   783.5   402.7  795.09   412.6  803.27   422.4  808.87   432.2  814.15
#Mann= 3 , 0 , 0
       0      .1       0   206.3    .045       0     231      .1       0
Bank Sta=206.3,231
XS Rating Curve= 0 ,0
Exp/Cntr=0.3,0.1

Type RM Length L Ch R = 1 ,1649    ,350.2,360.7,371.1
XS GIS Cut Line= 3
     1887402.475      534653.949     1887687.197      534523.741
     1887852.127      534259.852
#Sta/Elev= 30
       0  687.04     9.8  683.96    48.9   668.3    97.8  652.68   107.6   650.6
   127.2  648.34     137  646.51   166.3  636.64   195.7  631.33   205.5  630.37
   215.2  630.26   229.4631.1565   303.3  639.52     352  646.58   381.2  649.92
   390.9  651.57   400.6  653.73   410.3  657.01   429.8  664.81     459  673.11
   468.7  676.65   478.4   680.8   497.8   690.6   507.6  696.75   517.3  703.63
   536.8   719.8   556.2  737.25   575.6  753.85   595.1  768.04   624.3  787.04
#Mann= 3 , 0 , 0
       0      .1       0   195.7    .045       0   229.4      .1       0
Bank Sta=195.7,229.4
XS Rating Curve= 0 ,0
Exp/Cntr=0.3,0.1

Type RM Length L Ch R = 1 ,1288.3  ,363.8,391.3,418.2
XS GIS Cut Line= 2
     1887490.335      534906.973     1887855.916      534919.526
#Sta/Elev= 30
       0   664.2     9.6  662.47    19.2  660.08    28.9  656.28    38.5  652.94
    48.1  650.55    86.6  642.12   105.9  638.06   125.1  634.21   144.4  630.67
     154  628.63   163.6  625.66   173.3     623   182.9  622.06   192.5  622.58
   202.2  624.01   211.8  626.12   221.4  630.29     231  636.27   240.7   639.9
   250.3  640.15   259.9  641.93   269.5  647.88     308  678.81   317.7  684.83
   327.3  687.72   336.9  691.35   346.5  700.34   356.2  711.93   365.8  722.18
#Mann= 3 , 0 , 0
       0      .1       0   173.3    .045       0   202.2      .1       0
Bank Sta=173.3,202.2
XS Rating Curve= 0 ,0
Exp/Cntr=0.3,0.1

Type RM Length L Ch R = 1 ,897.1   ,40.4,40.1,39.8
XS GIS Cut Line= 4
     1887437.041      535117.002     1887515.687      535181.585
      1887549.02      535277.419     1887641.333      535357.026
#Sta/Elev= 30
       0  652.61    18.5  641.39    27.8  637.06      37  635.48    46.3   634.8
    55.5  633.82    64.8  632.56      74  631.71    83.3   631.2    92.5  630.07
     111  625.06   129.4  621.12   138.7  618.56     145617.2726   147.9  616.68
   157.1  616.22   166.3  617.15   175.6  621.44   184.8   627.6     194  631.76
   203.2  632.72     222   634.2   259.5  636.43   268.9  637.17   278.2   639.6
   287.6  644.83     297  651.36   306.4  657.52   315.8  659.54   325.1  659.46
#Mann= 3 , 0 , 0
       0      .1       0     145    .045       0   166.3      .1       0
Bank Sta=145,166.3
XS Rating Curve= 0 ,0
Exp/Cntr=0.3,0.1

Type RM Length L Ch R = 1 ,857     ,37.7,37.7,37.7
XS GIS Cut Line= 4
     1887416.728      535120.127     1887472.859      535183.191
     1887525.949      535329.709     1887590.687      535366.481
#Sta/Elev= 30
       0  664.94     9.4  659.25    18.8  653.35    28.1  647.81    46.9  637.24
    56.3  633.82    65.7  631.95      75  631.58    84.4  631.01    94.2  630.11
   103.9   628.6   113.6  626.34   123.4  623.39   133.1  619.63   142.1616.8749
   142.9  616.63   152.6  616.02   162.4  616.66   172.1  620.03   181.8  623.91
   191.6  626.68   201.3  628.99     211  630.95   220.8   632.5   240.3  634.34
   258.9  636.23   268.2  636.88   296.1  637.74   305.4  638.22   314.7  639.87
#Mann= 3 , 0 , 0
       0      .1       0   142.1    .045       0   162.4      .1       0
Bank Sta=142.1,162.4
XS Rating Curve= 0 ,0
Exp/Cntr=0.3,0.1

Type RM Length L Ch R = 1 ,819.2   ,145.9,132.7,119.2
XS GIS Cut Line= 4
     1887384.958      535156.065     1887445.588      535218.487
     1887487.238      535333.432     1887572.679       535382.24
#Sta/Elev= 30
       0  672.28     9.7  664.61    19.3  657.27      29   651.4    38.7  647.76
    48.3  644.97      58  641.99    67.7  638.58    77.4  633.75      87  629.82
    96.4  626.97   105.8  623.78   115.2  619.22   122.6616.9291   124.6  616.31
     134  615.66   143.4  617.39   152.8  620.83   162.3  624.13   171.7  625.78
   181.1  626.35   209.3  627.09   219.1   628.3     229  630.82   238.8  633.52
   248.6  635.31   258.5  636.39   268.3  637.07   297.8  637.82   307.7  638.33
#Mann= 3 , 0 , 0
       0      .1       0   122.6    .045       0   143.4      .1       0
Bank Sta=122.6,143.4
XS Rating Curve= 0 ,0
Exp/Cntr=0.3,0.1

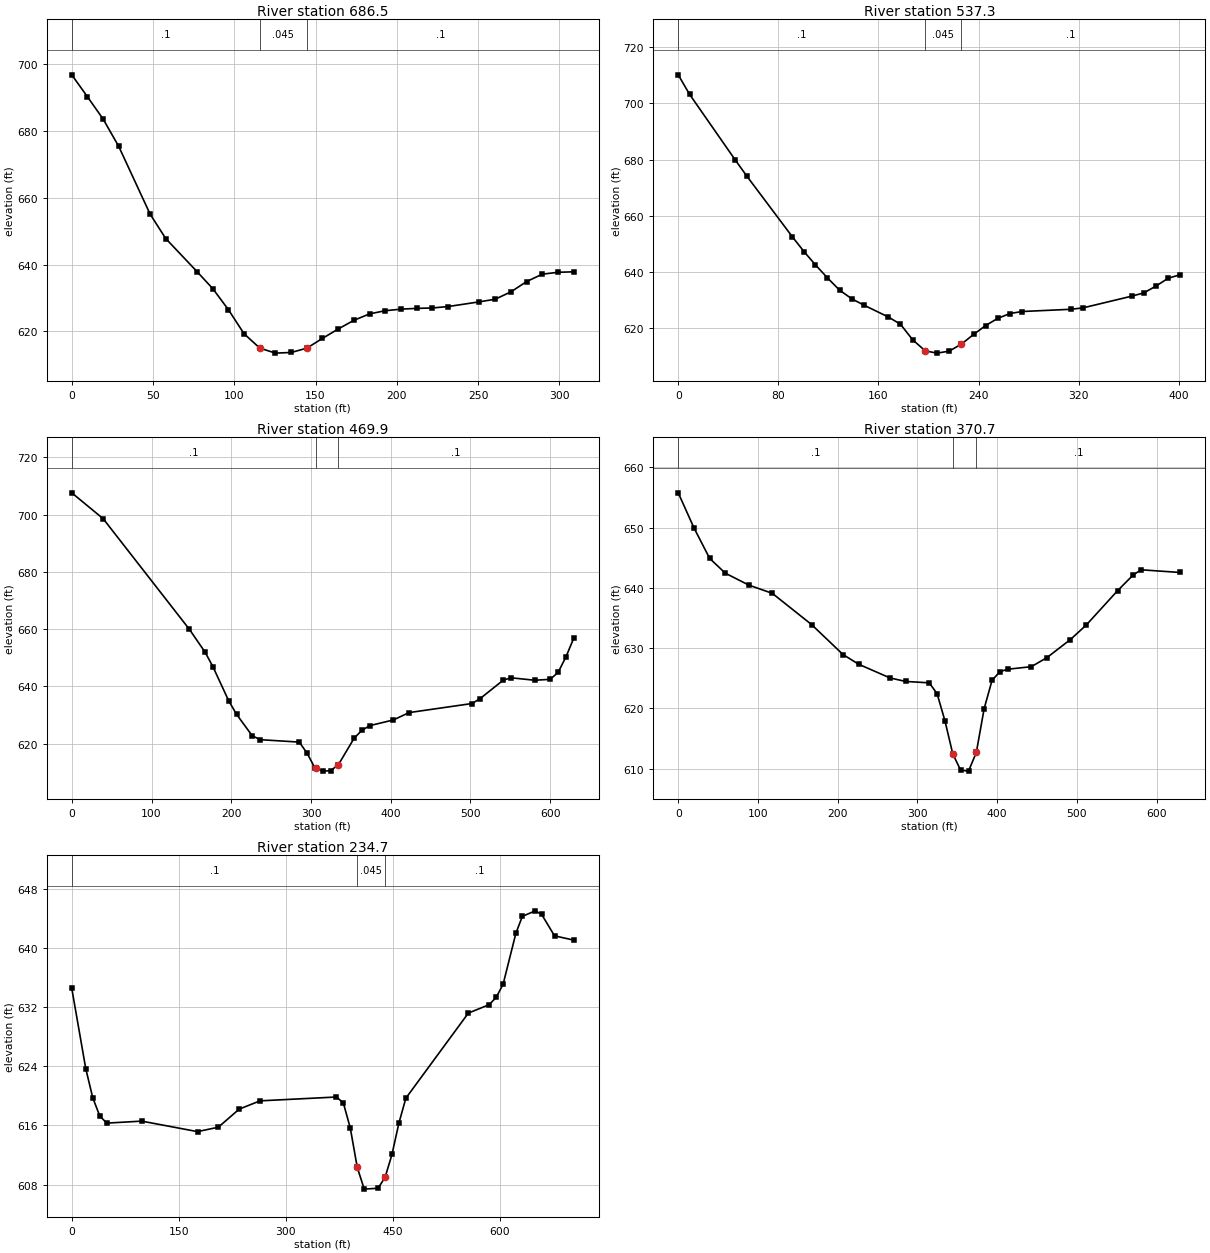
Type RM Length L Ch R = 1 ,686.5   ,154.3,149.2,144
XS GIS Cut Line= 3
     1887265.079      535280.544     1887443.898       535411.62
     1887524.628      535444.606
#Sta/Elev= 30
       0  696.84     9.6   690.3    19.3  683.58    28.9   675.4    48.2  655.12
    57.8  647.82    77.1  637.89    86.8  632.78    96.4  626.49     106   619.3
   115.7     615   125.3   613.5     135   613.7   144.6  614.98   154.2   617.9
   163.9  620.72   173.5  623.31   183.2  625.25   192.8   626.2   202.4  626.66
   212.1   626.9   221.7  627.02   231.4  627.44   250.8  628.86   260.5  629.65
   270.2  631.85   279.8  634.92   289.5  637.15   299.2  637.71   308.9  637.85
#Mann= 3 , 0 , 0
       0      .1       0   115.7    .045       0   144.6      .1       0
Bank Sta=115.7,144.6
XS Rating Curve= 0 ,0
Exp/Cntr=0.3,0.1

Type RM Length L Ch R = 1 ,537.3   ,65.6,67.4,69.1
XS GIS Cut Line= 3
     1887137.475      535383.842     1887220.808      535455.023
     1887489.037      535569.606
#Sta/Elev= 30
       0  710.14     9.1  703.18    45.7   679.8    54.8  674.16    91.3  652.53
   100.5  647.34   109.6  642.64   119.3  637.96     129   633.6   138.8  630.52
   148.5  628.27   167.9  624.09   177.6  621.52   187.4  615.97   197.4612.0539
   206.8  611.24   216.5  611.94   226.3  614.43     236  617.86   245.7  621.04
   255.4   623.6   265.2  625.32   274.9  626.03   313.8  626.82   323.5  627.32
   362.4  631.48   372.1  632.64   381.8  635.05   391.6  637.86   401.3  639.12
#Mann= 3 , 0 , 0
       0      .1       0   197.4    .045       0   226.3      .1       0
Bank Sta=197.4,226.3
XS Rating Curve= 0 ,0
Exp/Cntr=0.3,0.1

Type RM Length L Ch R = 1 ,469.9   ,98.8,99.1,99.7
XS GIS Cut Line= 2
     1887013.461      535413.294     1887572.758      535702.309
#Sta/Elev= 30
       0  707.59    39.4  698.54   147.6  659.86   167.2  651.91   177.1  646.79
   196.7  634.98   206.6  630.22   226.2  622.75   236.1  621.35   285.3   620.5
   295.1  616.63   304.9  611.46   306.4611.2933   314.8  610.36   324.6   610.5
   334.4  612.63   354.1  621.87     364  624.66   373.8  626.26   403.3  628.24
     423  630.81   501.7  633.97   511.5  635.57     541  642.13   550.9  642.97
   580.4  642.11     600  642.43   609.9  644.87   619.7  650.28   629.6  656.88
#Mann= 3 , 0 , 0
       0      .1       0   306.4    .045       0   334.4      .1       0
Bank Sta=306.4,334.4
XS Rating Curve= 0 ,0
Exp/Cntr=0.3,0.1

Type RM Length L Ch R = 1 ,370.7   ,136.6,136,135.3
XS GIS Cut Line= 2
     1886953.577      535482.052     1887505.683      535784.577
#Sta/Elev= 30
       0  655.76    19.7  649.95    39.4  644.88      59  642.43    88.5  640.45
     118  639.08   167.2   633.9   206.6  628.93   226.2  627.32   265.6  625.04
   285.3  624.46   314.8  624.23   324.6  622.43   334.4  617.95   344.3  612.42
   354.1  609.75     364  609.58   373.8  612.68   383.6  619.94   393.5  624.64
   403.3  626.08   413.2  626.49   442.7  626.91   462.3  628.41   491.8  631.42
   511.5   633.8   550.9  639.52   570.5  642.13   580.4  642.99   629.6  642.54
#Mann= 3 , 0 , 0
       0      .1       0   344.3    .045       0   373.8      .1       0
Bank Sta=344.3,373.8
XS Rating Curve= 0 ,0
Exp/Cntr=0.3,0.1

Type RM Length L Ch R = 1 ,234.7   ,225.4,234.7,244.1
XS GIS Cut Line= 4
     1886893.577      535522.222     1886953.256      535645.919
     1887369.464      535858.451     1887466.494      535879.209
#Sta/Elev= 30
       0  634.53    19.6  623.69    29.4  619.75    39.2   617.3      49  616.32
    98.1  616.59   176.3  615.17   205.5  615.77   234.7  618.21   263.9  619.33
     371  619.85   380.7  619.06   390.5  615.65   400.2  610.36     410   607.4
   429.4  607.52   439.2  608.98   448.9  612.08   458.6  616.31   468.4  619.69
     556  631.19   585.2  632.33   594.9   633.3   604.7  635.08   622.7     642
   631.7  644.26   649.8  645.01   658.8  644.52   676.8  641.63   703.9  641.05
#Mann= 3 , 0 , 0
       0      .1       0   400.2    .045       0   439.2      .1       0
Bank Sta=400.2,439.2
XS Rating Curve= 0 ,0
Exp/Cntr=0.3,0.1

Chan Stop Cuts=-1
Use User Specified Reach Order=0
Composite Channel Slope=5